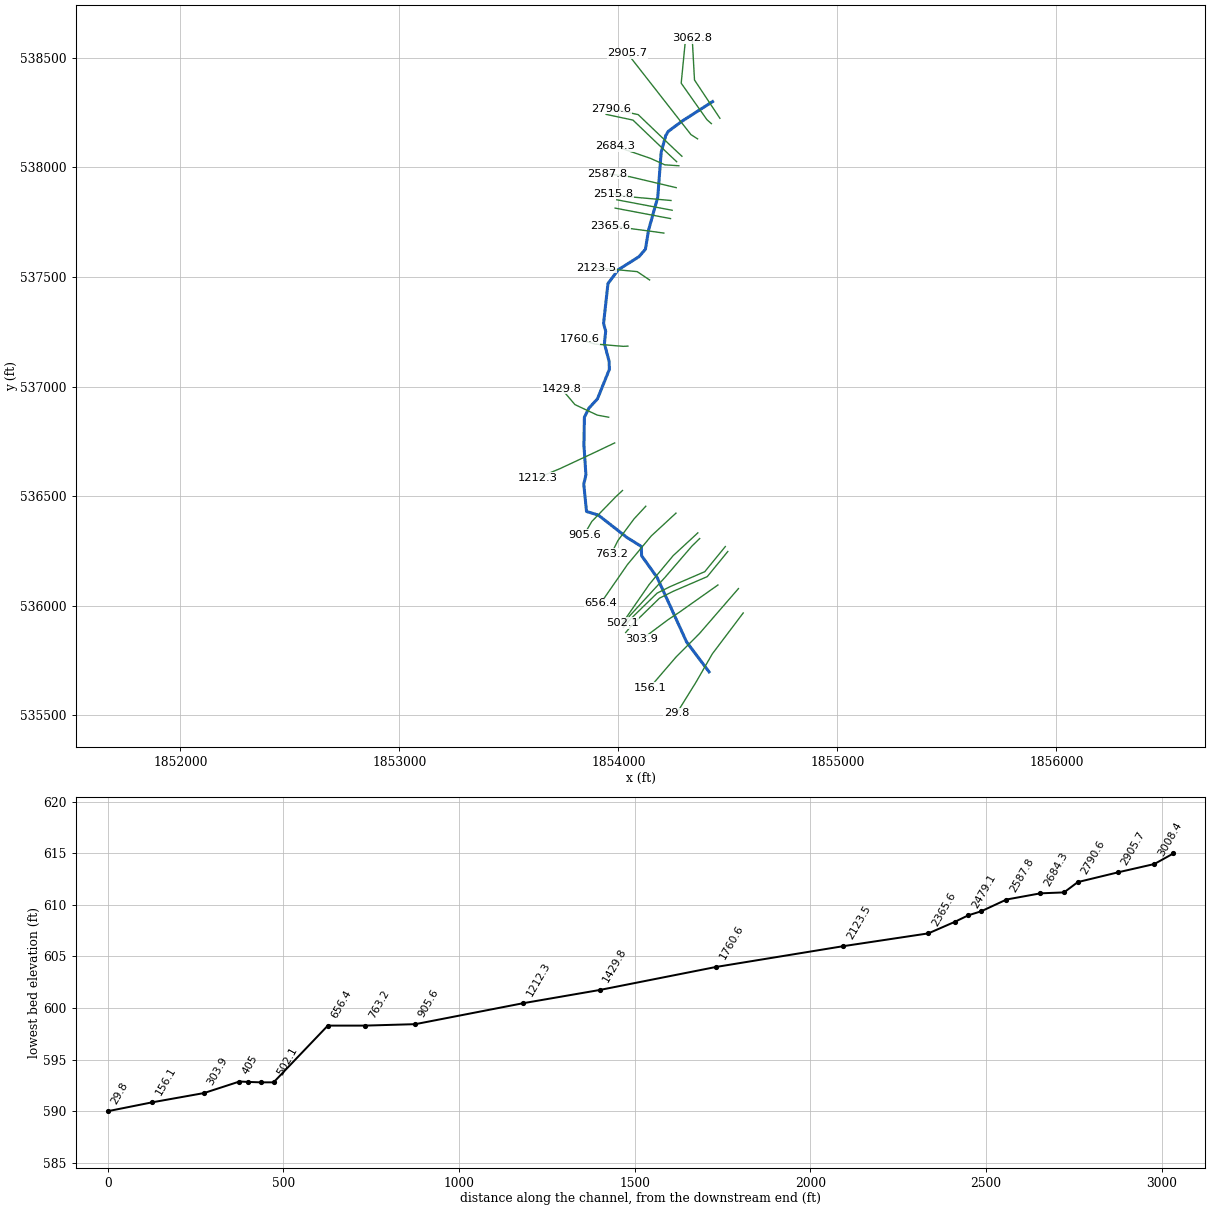
--- JORDANCR.prj (project) ---

Proj Title=JORDANCR
Current Plan=p01
Default Exp/Contr=0,0
English Units
Geom File=g01
Flow File=f01
Plan File=p01
BEGIN DESCRIPTION:
END DESCRIPTION:
DSS Export Rating Curves= 0
DSS Export Rating Curve Sorted= 0
DSS Export Volume Flow Curves= 0
DXF OffsetX= 0
DXF OffsetY= 0
DXF ScaleX= 0
DXF ScaleY= 0

--- JORDANCR.p01 (plan) ---

Plan Title=Floodplain
Program Version=4.00
Geom File=g01
Flow File=f01
K Sum by GR=0
Std Step Tol=0.01
Critical Tol=0.01
Num of Std Step Trials=20
Max Error Tol=0.3
Flow Tol Ratio=0.001
Split Flow NTrial=30
Split Flow Tol=0.02
Split Flow Ratio=0.02
Log Output Level=0
Friction Slope Method=1
Unsteady Friction Slope Method=2
Unsteady Bridges Friction Slope Method=1
Global Log Level=0
CheckData=False
Run HTab=0
Run UNet=0
Run PostProcess=0
UNET Theta=0
UNET Theta Warmup=0
UNET ZTol=0
UNET ZSATol=0
UNET MxIter=0
UNET MaxInSteps=0
UNET DtIC=0
UNET DtMin=0
UNET MaxCRTS=0
UNET WFStab=0
UNET SFStab=0
UNET WFX=0
UNET SFX=0
UNET DSS MLevel=0
UNET DZMax Abort=0
UNET Convert EG Bridges=0
UNET Use Existing IB Tables=0
UNET Froude Limit=0
UNET Froude Power=0
Write IC File=0
Echo Input=False
Echo Output=False
Write Detailed=0

--- JORDANCR.f01 (steady flow) ---

Flow Title=NFF Regression Equation
Program Version=4.10
Number of Profiles= 1
Profile Names=P100yr
River Rch & RM=JORDANCR,Main            ,3062.8
853.8513
River Rch & RM=JORDANCR,Main            ,2684.3
1060.186
River Rch & RM=JORDANCR,Main            ,430.2
 1138.59
Boundary for River Rch & Prof#=JORDANCR,Main            , 1
Up Type= 0
Dn Type= 3
Dn Slope=0.007
DSS Import GetInterval= 0
DSS Import GetPeak= 0
DSS Import FillOption= 0

--- JORDANCR.g01 (geometry) ---

Geom Title=USGS 10m DEM
Program Version=4.10

River Reach=JORDANCR        ,Main
Reach XY= 30
     1854429.995      538299.452     1854291.106      538210.563
     1854227.912      538164.035     1854216.106      538144.591
     1854195.273      538068.202     1854179.604      537863.384
      1854137.58      537713.059     1854123.418      537626.335
     1854093.884      537592.117     1853999.545      537532.764
     1853952.323      537469.569     1853932.184      537287.625
     1853941.906      537252.208     1853936.181      537195.989
     1853957.878      537113.319     1853958.573      537077.903
     1853904.406      536943.875     1853865.517      536901.514
     1853844.684      536859.847     1853842.601      536732.069
     1853851.628      536597.347     1853841.906      536554.291
     1853854.406      536429.986     1853907.878      536414.014
     1854038.434       536311.93      1854104.53      536270.789
      1854105.82      536228.185     1854176.744      536129.486
     1854311.351      535834.847     1854413.851      535698.792

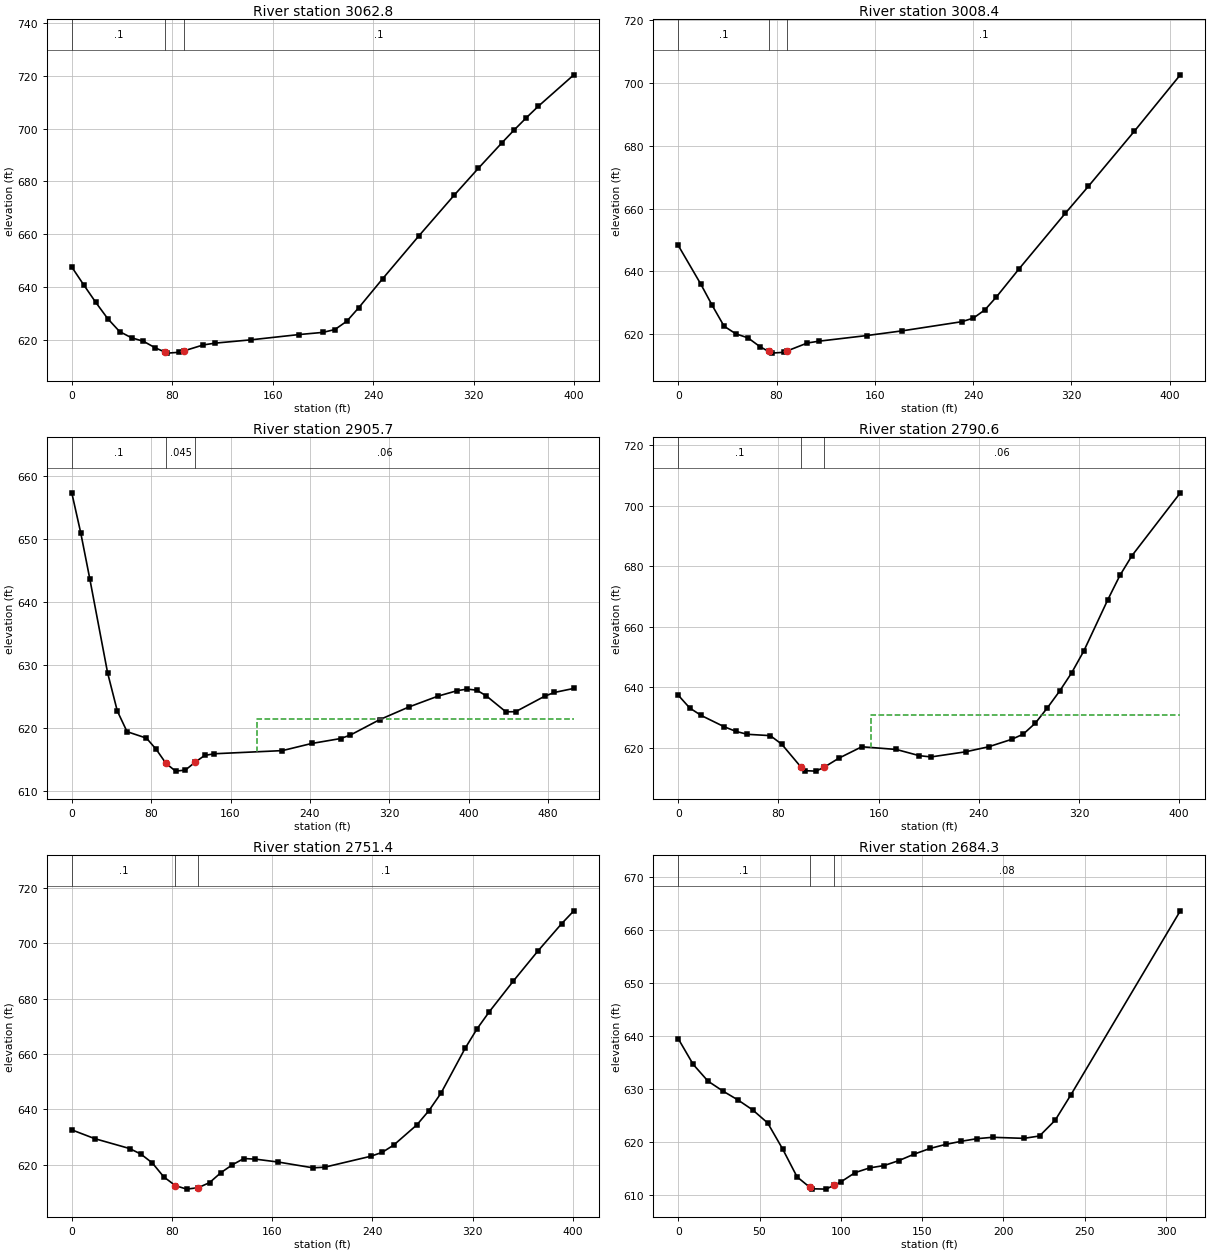
Type RM Length L Ch R = 1 ,3062.8  ,53.8,54.4,55.1
XS GIS Cut Line= 3
     1854463.306       538223.41     1854347.421       538397.89
     1854337.004      538587.994
#Sta/Elev= 29
       0   647.6     9.5  640.85      19  634.29    28.6  628.06    38.1  623.15
    47.6   620.8    57.1  619.47    66.6  616.96    74.2   615.4    76.2  614.99
    85.7  615.31    89.2  615.82   104.7  618.09   114.2  618.78   142.8  620.03
   180.9  622.02   199.9  622.84   209.5  623.92     219  627.07   228.5  632.18
   247.5  643.13   276.1  659.22   304.6  674.84   323.7  684.95   342.7  694.72
   352.2  699.45   361.8  704.04   371.3  708.38   399.8  720.37
#Mann= 3 , 0 , 0
       0      .1       0    74.2    .045       0    89.2      .1       0
Bank Sta=74.2,89.2
XS Rating Curve= 0 ,0
Exp/Cntr=0.3,0.1

Type RM Length L Ch R = 1 ,3008.4  ,101.4,102.7,103.7
XS GIS Cut Line= 4
     1854424.461      538198.888     1854403.845      538217.334
     1854286.657       538383.35     1854304.018      538560.216
#Sta/Elev= 24
       0  648.27    18.4  635.91    27.7  629.13    37.3  622.54      47  620.08
    56.7  618.84    66.4  616.05    73.5   614.5      76  613.96    85.7  614.22
    88.5  614.64   105.1  617.19   114.8  617.78   153.5  619.56   182.5  621.07
   230.9  623.98   240.2  625.12   249.6  627.75   258.9  631.84   277.6  640.91
     315   658.5   333.8   667.1   371.2  684.64   408.6   702.6
#Mann= 3 , 0 , 0
       0      .1       0    73.5    .045       0    88.5      .1       0
Bank Sta=73.5,88.5
XS Rating Curve= 0 ,0
Exp/Cntr=0.3,0.1

Type RM Length L Ch R = 1 ,2905.7  ,112.7,115.1,117.5
XS GIS Cut Line= 3
     1854361.527      538129.443     1854331.145      538148.975
     1854041.431      538518.983
#Sta/Elev= 30
       0  657.37       9  651.04    18.1  643.76    36.1  628.78    45.9  622.71
    55.7  619.43    75.3   618.4    85.1  616.62    94.9   614.4   104.6  613.16
   114.4  613.32   124.2  614.56     134  615.66   143.8  615.92   212.3  616.42
   241.7  617.55   271.1  618.34   280.9   618.9   310.2  621.33   339.6  623.34
     369  625.07   388.6  625.95   398.4  626.19   408.2  626.02   417.9   625.1
   437.5  622.58   447.3   622.6   476.7  625.07   486.5  625.66     506   626.3
#Mann= 3 , 0 , 0
       0      .1       0    94.9    .045       0   124.2     .06       0
#XS Ineff= 2 , 0
                          186.89          621.44
Permanent Ineff=
       F       F
Bank Sta=94.9,124.2
XS Rating Curve= 0 ,0
Exp/Cntr=0.3,0.1

Type RM Length L Ch R = 1 ,2790.6  ,39.2,39.2,39.2
XS GIS Cut Line= 5
     1854289.912      538050.233     1854256.275        538081.7
     1854190.086      538144.634      1854090.26       538240.12
     1853967.647      538266.162
#Sta/Elev= 30
       0  637.33     9.2  633.08    18.4  630.61    36.8  626.87    46.1  625.35
    55.2  624.39    73.5  623.95    82.6  621.14   97.87  613.62   100.9  612.36
     110  612.21   116.4  613.48   128.3   616.5   146.6  620.27   174.2  619.37
   192.6  617.31   201.9  616.91   229.5   618.6   247.9  620.27   266.3  622.73
   275.5  624.45   285.2  628.11   294.8  633.17   304.5  638.66   314.1   644.7
   323.8  651.91     343   668.9   352.7  676.96   362.3  683.48   400.9  704.26
#Mann= 3 , 0 , 0
       0      .1       0   97.87    .045       0   116.4     .06       0
#XS Ineff= 2 , 0
                          154.12          630.77
Permanent Ineff=
       F       F
Bank Sta=97.87,116.4
XS Rating Curve= 0 ,0
Exp/Cntr=0.3,0.1

Type RM Length L Ch R = 1 ,2751.4  ,58.8,67.1,75.8
XS GIS Cut Line= 5
     1854266.041      538025.277     1854232.404      538056.744
     1854166.214      538119.678     1854066.388      538215.164
     1853943.775      538241.206
#Sta/Elev= 30
       0  632.61    18.4  629.43    46.1  625.88    55.2  623.86    64.3  620.67
    73.5  615.61    82.7  612.49    91.7  611.21   100.9  611.72     110  613.55
   119.1  617.16   128.3  620.02   137.4  622.26   146.6  622.04     165  620.98
   192.6   618.9   201.9  619.13   238.7  623.07   247.9  624.49   257.1  627.13
   275.5  634.39   285.2  639.56   294.8  645.85   314.1  662.07   323.8  669.21
   333.4  675.27   352.7  686.41     372  697.08   391.2  707.09   400.9   711.7
#Mann= 3 , 0 , 0
       0      .1       0    82.7    .045       0   100.9      .1       0
Bank Sta=82.7,100.9
XS Rating Curve= 0 ,0
Exp/Cntr=0.3,0.1

Type RM Length L Ch R = 1 ,2684.3  ,91.6,96.6,100.4
XS GIS Cut Line= 4
     1854275.806      538006.831     1854211.787      538011.171
     1854146.683      538040.468     1853982.838      538096.891
#Sta/Elev= 29
       0  639.53     9.2  634.68    18.3  631.52    27.5  629.64    36.7  627.97
    45.8  626.08      55  623.62    64.2  618.71    73.1  613.43    80.9  611.47
      82  611.19    90.9  611.12    95.9  611.86    99.9  612.46   108.8  614.24
   117.7  615.13   126.6  615.57   135.6   616.5   145.2  617.74   154.8   618.8
   164.4  619.56   174.1  620.16   183.7  620.65   193.3  620.91   212.6  620.71
   222.2  621.16   231.8  624.12   241.5  628.93   308.8  663.69
#Mann= 3 , 0 , 0
       0      .1       0    80.9    .045       0    95.9     .08       0
Bank Sta=80.9,95.9
XS Rating Curve= 0 ,0
Exp/Cntr=0.3,0.1

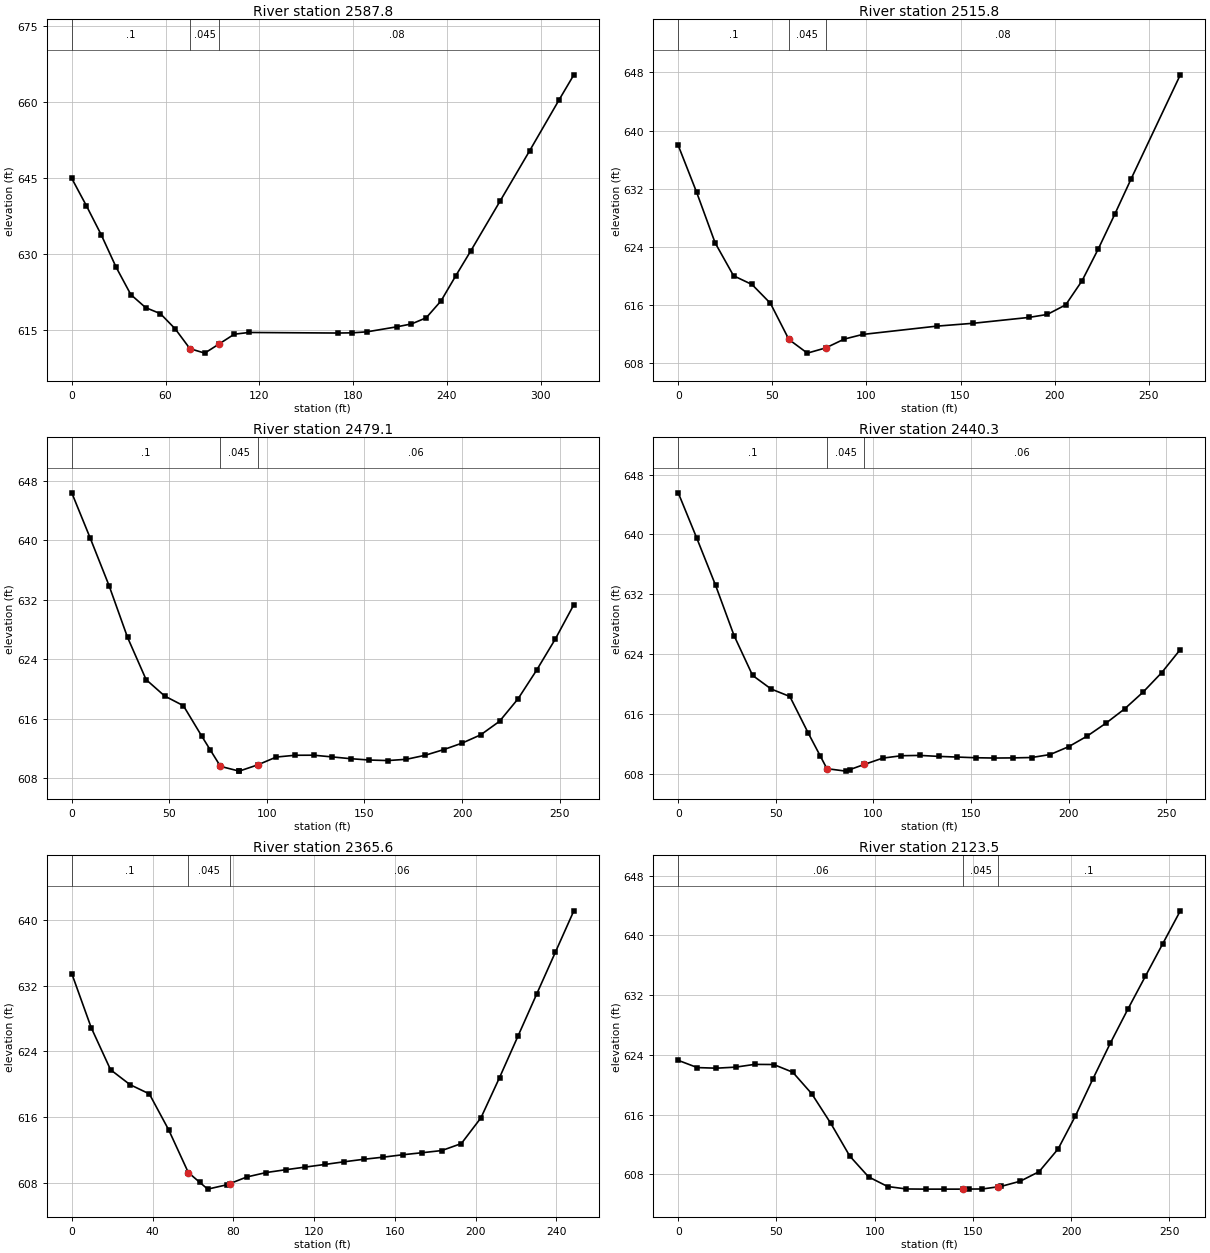
Type RM Length L Ch R = 1 ,2587.8  ,68.7,72,75.2
XS GIS Cut Line= 3
     1854263.871      537907.004     1854052.282      537956.917
     1853949.201      537969.938
#Sta/Elev= 26
       0  644.95     9.4  639.54    18.9  633.81    28.4  627.44    37.8  622.05
    47.3  619.48    56.7   618.3    66.2   615.3    75.6   611.4    85.1  610.52
    94.5  612.37     104  614.25   113.4  614.59   170.1  614.48   179.6  614.52
     189  614.72   207.9   615.7   217.4  616.27   226.8  617.48   236.3  620.81
   245.7  625.74   255.2  630.59   274.1  640.48     293  650.39   311.8   660.4
   321.3  665.36
#Mann= 3 , 0 , 0
       0      .1       0    75.6    .045       0    94.5     .08       0
Bank Sta=75.6,94.5
XS Rating Curve= 0 ,0
Exp/Cntr=0.3,0.1

Type RM Length L Ch R = 1 ,2515.8  ,38.9,36.7,34.5
XS GIS Cut Line= 3
     1854239.999       537848.41     1854034.921      537866.857
     1853975.242      537878.792
#Sta/Elev= 21
       0  637.95     9.8  631.49    19.6  624.55    29.4  620.02    39.2  618.82
      49  616.23    58.8  611.26    68.6  609.38    78.4   610.1    88.2  611.31
      98  611.95   137.3  613.09   156.9  613.49   186.3  614.29   196.1   614.7
   205.9  616.02   214.6  619.34   223.3  623.76     232   628.5   240.7  633.37
   266.8  647.66
#Mann= 3 , 0 , 0
       0      .1       0    58.8    .045       0    78.4     .08       0
Bank Sta=58.8,78.4
XS Rating Curve= 0 ,0
Exp/Cntr=0.3,0.1

Type RM Length L Ch R = 1 ,2479.1  ,38.8,38.8,38.8
XS GIS Cut Line= 2
     1854245.425      537803.923     1853992.603      537851.666
#Sta/Elev= 30
       0  646.37     9.5  640.26    19.1  633.91    28.6  626.94    38.1  621.28
    47.6  619.08    57.2  617.78    66.7  613.65    70.9  611.87    76.2  609.63
    85.8  608.99    85.9     609    95.3  609.83   104.8  610.88   114.4  611.12
   123.9  611.13   133.4   610.9   142.9  610.66   152.5  610.48     162  610.41
   171.5  610.58   181.1  611.12   190.6  611.88   200.1  612.76   209.6  613.87
   219.2  615.68   228.7   618.7   238.2  622.54   247.8  626.73   257.3  631.35
#Mann= 3 , 0 , 0
       0      .1       0    76.2    .045       0    95.3     .06       0
Bank Sta=76.2,95.3
XS Rating Curve= 0 ,0
Exp/Cntr=0.3,0.1

Type RM Length L Ch R = 1 ,2440.3  ,73.5,74.8,75.9
XS GIS Cut Line= 2
     1854237.829      537765.945     1853985.008      537813.688
#Sta/Elev= 30
       0  645.56     9.5   639.5    19.1  633.22    28.6  626.48    38.1  621.15
    47.6  619.33    57.2  618.33    66.7   613.4    72.8  610.37    76.2  608.68
    85.8  608.35    87.8  608.54    95.3  609.24   104.8  610.09   114.4  610.41
   123.9  610.45   133.4  610.32   142.9  610.23   152.5  610.14     162   610.1
   171.5  610.12   181.1  610.17   190.6  610.57   200.1  611.62   209.6  613.04
   219.2  614.76   228.7  616.66   238.2  618.91   247.8  621.53   257.3  624.61
#Mann= 3 , 0 , 0
       0      .1       0    76.2    .045       0    95.3     .06       0
Bank Sta=76.2,95.3
XS Rating Curve= 0 ,0
Exp/Cntr=0.3,0.1

Type RM Length L Ch R = 1 ,2365.6  ,235.3,242,244.9
XS GIS Cut Line= 4
     1854207.447      537699.756      1854169.47      537705.181
     1854006.709      537726.883     1853961.136      537733.393
#Sta/Elev= 29
       0  633.45     9.6  626.89    19.2  621.76    28.8  619.95    38.4  618.82
      48  614.44    57.7  609.26    63.4  608.06    67.3  607.24      77  607.78
    78.4  607.92    86.7  608.72    96.3  609.26     106   609.6   115.6  609.92
   125.3  610.24     135  610.57   144.6  610.87   154.3  611.13   163.9  611.42
   173.6  611.67   183.2  611.93   192.9  612.78   202.6  615.91   211.8   620.8
     221  625.88   230.2  630.96   239.4  636.02   248.6  641.08
#Mann= 3 , 0 , 0
       0      .1       0    57.7    .045       0    78.4     .06       0
Bank Sta=57.7,78.4
XS Rating Curve= 0 ,0
Exp/Cntr=0.3,0.1

Type RM Length L Ch R = 1 ,2123.5  ,369,362.9,360.2
XS GIS Cut Line= 4
     1854142.343      537485.997     1854085.919      537523.975
     1853961.136       537535.91     1853899.287      537542.421
#Sta/Elev= 30
       0  623.26     9.7  622.29    19.4  622.21    29.2  622.35    38.9  622.72
    48.6   622.7    58.3  621.67      68  618.77    77.7   614.8    87.3  610.44
    96.9  607.64   106.6  606.35   116.2  606.02   125.9     606   135.5     606
   145.2     606   147.8  606.01   154.8  606.02   162.8  606.31   164.4  606.37
   174.1  607.06   183.7  608.34   193.4  611.39   202.2  615.81   211.1  620.77
     220  625.58   228.9  630.12   237.8  634.52   246.7  638.91   255.6   643.3
#Mann= 3 , 0 , 0
       0     .06       0   145.2    .045       0   162.8      .1       0
Bank Sta=145.2,162.8
XS Rating Curve= 0 ,0
Exp/Cntr=0.3,0.1

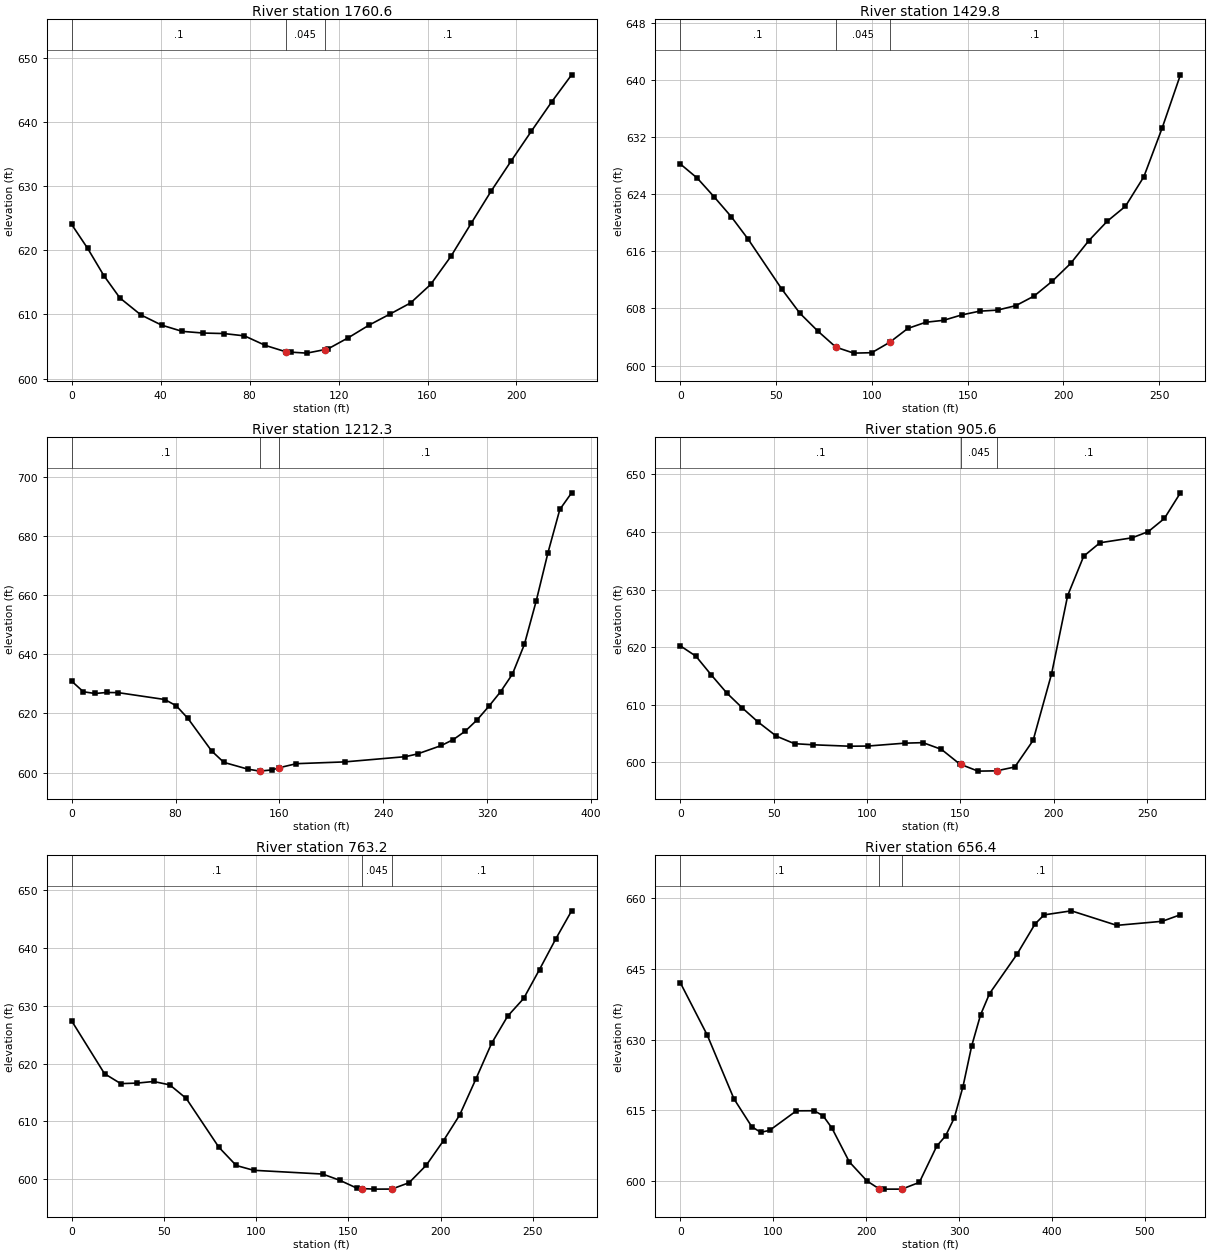
Type RM Length L Ch R = 1 ,1760.6  ,337.7,330.8,322.7
XS GIS Cut Line= 4
     1854043.602      537184.348       1854021.9      537183.263
     1853891.692      537194.114     1853822.247       537214.73
#Sta/Elev= 28
       0  624.02     7.2  620.29    14.5  616.04    21.7  612.57    31.1  609.94
    40.4  608.35    49.7  607.37    59.1  607.11    68.4  607.03    77.7  606.67
    87.1  605.18    96.4  604.18    98.7  604.13   105.7  603.98   113.7  604.52
   115.1  604.61   124.4  606.38   133.7  608.34   143.1  610.06   152.4   611.8
   161.4  614.67   170.5  619.04   179.6  624.18   188.6  629.21   197.7  633.96
   206.7  638.55   215.8   643.1   224.8  647.33
#Mann= 3 , 0 , 0
       0      .1       0    96.4    .045       0   113.7      .1       0
Bank Sta=96.4,113.7
XS Rating Curve= 0 ,0
Exp/Cntr=0.3,0.1

Type RM Length L Ch R = 1 ,1429.8  ,197.1,217.6,237.3
XS GIS Cut Line= 4
     1853955.711      536859.912     1853903.628      536869.678
     1853801.631      536917.421     1853739.782       536990.12
#Sta/Elev= 28
       0   628.2     8.8  626.23    17.7  623.58    26.5  620.85    35.3  617.71
      53  610.68    62.4  607.32    71.8  604.82    81.2  602.58    90.5  601.75
    99.9  601.81   109.3  603.27   118.7   605.2   128.1  606.07   137.4  606.34
   146.8  607.09   156.2  607.62   165.6  607.77   175.2   608.4   184.7  609.74
   194.2  611.82   203.8  614.31   213.3   617.5   222.9  620.21   232.4   622.3
     242  626.43   251.5   633.2   261.1  640.69
#Mann= 3 , 0 , 0
       0      .1       0    81.2    .045       0   109.3      .1       0
Bank Sta=81.2,109.3
XS Rating Curve= 0 ,0
Exp/Cntr=0.3,0.1

Type RM Length L Ch R = 1 ,1212.3  ,296.1,306.7,315.2
XS GIS Cut Line= 4
     1853982.838      536742.725     1853893.862      536700.407
     1853733.272      536625.537      1853632.36      536583.219
#Sta/Elev= 30
       0  630.87       9  627.29    17.9   626.7    26.9  627.04    35.8  626.99
    71.7  624.67    80.6  622.54    89.6  618.26   107.8   607.3   117.2  603.43
   135.8  601.13     145  600.47   154.5   600.9     160  601.63   173.1  602.99
   210.4  603.59   257.1  605.36   266.4  606.28   284.8  609.13     294  611.14
   303.1  613.95   312.2  617.74   321.3  622.35   330.4  627.31   339.5  633.24
   348.7  643.27   357.8  657.92   366.9   674.3     376  688.87   385.1   694.5
#Mann= 3 , 0 , 0
       0      .1       0     145    .045       0     160      .1       0
Bank Sta=145,160
XS Rating Curve= 0 ,0
Exp/Cntr=0.3,0.1

Type RM Length L Ch R = 1 ,905.6   ,139.3,142.3,145.8
XS GIS Cut Line= 4
     1854018.645      536525.711     1853988.263      536497.499
     1853878.671      536384.652     1853843.949      536324.973
#Sta/Elev= 28
       0   620.2     8.3  618.41    16.6  615.12    24.9  611.99    33.2   609.4
    41.5     607    51.3  604.53    61.1  603.21      71  603.02    90.6  602.77
   100.4   602.8   120.1   603.3   129.9  603.39   139.8  602.22   149.6  599.67
   150.1  599.61   159.4  598.44   169.3  598.49   179.1  599.16   188.9  603.78
   198.8  615.37   207.4  628.95     216   635.8   224.7  638.13   241.9  638.99
   250.6  640.07   259.2  642.35   267.8  646.81
#Mann= 3 , 0 , 0
       0      .1       0   150.1    .045       0   169.3      .1       0
Bank Sta=150.1,169.3
XS Rating Curve= 0 ,0
Exp/Cntr=0.3,0.1

Type RM Length L Ch R = 1 ,763.2   ,107.6,106.8,117
XS GIS Cut Line= 4
     1854124.982      536454.096     1854070.728      536395.502
     1853998.029      536297.846     1853966.562      536235.997
#Sta/Elev= 27
       0   627.4    17.8  618.27    26.6  616.55    35.5  616.64    44.4  616.92
    53.2  616.33    62.1  613.99    79.8  605.54    89.2  602.39    98.6  601.56
     136  600.91   145.4  599.82   154.8  598.44   157.2   598.4   164.1   598.3
   173.5  598.31   182.9  599.41   192.2  602.43   201.6  606.71   210.3  611.11
     219  617.27   227.6   623.5   236.3  628.21     245  631.28   253.6  636.29
   262.3  641.52     271  646.44
#Mann= 3 , 0 , 0
       0      .1       0   157.2    .045       0   173.5      .1       0
Bank Sta=157.2,173.5
XS Rating Curve= 0 ,0
Exp/Cntr=0.3,0.1

Type RM Length L Ch R = 1 ,656.4   ,154,154.3,143.1
XS GIS Cut Line= 4
     1854262.786      536422.629     1854149.938      536318.463
     1854041.431      536188.254     1853918.819      536011.388
#Sta/Elev= 30
       0     642    28.8  630.97    57.6  617.44    76.8  611.53    86.4  610.34
      96  610.76   124.8   614.9     144  614.92   153.6  613.84     163  611.27
   181.8  604.08   200.7  600.05     214  598.35   219.5   598.3   238.3   598.3
   257.2  599.73     276  607.44   285.4  609.57   294.8  613.38   304.2  620.05
   313.6  628.69   323.1  635.24   332.8  639.76   362.2  648.05   381.8  654.52
   391.5  656.44   420.9   657.3   469.8  654.22   518.7  655.08   538.3  656.47
#Mann= 3 , 0 , 0
       0      .1       0     214    .045       0   238.3      .1       0
Bank Sta=214,238.3
XS Rating Curve= 0 ,0
Exp/Cntr=0.3,0.1

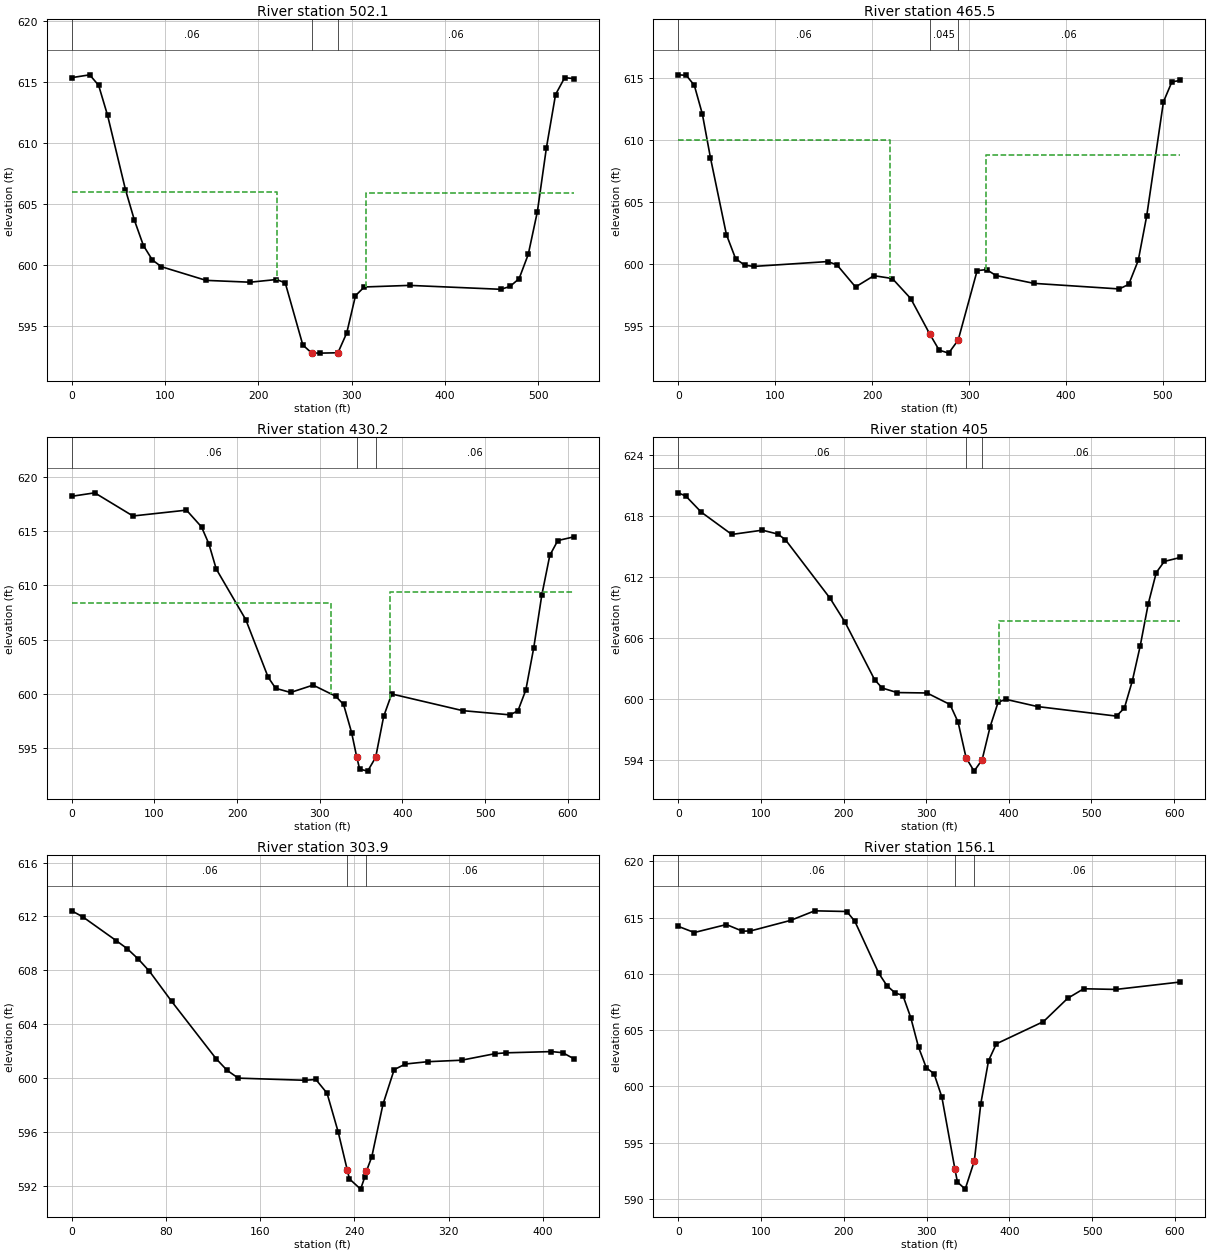
Type RM Length L Ch R = 1 ,502.1   ,37,36.6,35.6
XS GIS Cut Line= 4
     1854362.612      536332.568     1854249.765      536228.402
     1854141.258      536098.193     1854018.645      535921.327
#Sta/Elev= 30
       0  615.33    19.2  615.56    28.8   614.7    38.4  612.24    57.6  606.16
    67.2  603.66    76.8   601.6    86.4  600.42      96  599.87     144  598.75
   191.2   598.6   219.5  598.82   228.9  598.54   247.7  593.47   257.2  592.81
   266.6   592.8   285.4  592.83   294.8  594.45   304.2   597.5   313.6  598.21
   362.2  598.34     460  598.02   469.8  598.25   479.6  598.89   489.4  600.87
   499.2  604.37   508.9   609.6   518.7  613.95   528.5  615.33   538.3  615.25
#Mann= 3 , 0 , 0
       0     .06       0   257.2    .045       0   285.4     .06       0
#XS Ineff= 2 , 0
          220.02  605.99  315.15          605.92
Permanent Ineff=
       F       F
Bank Sta=257.2,285.4
XS Rating Curve= 0 ,0
Exp/Cntr=0.3,0.1

Type RM Length L Ch R = 1 ,465.5   ,44.2,35.3,26.7
XS GIS Cut Line= 5
     1854370.951      536306.663     1854335.361      536271.941
     1854211.229      536127.843     1854052.375        535955.1
     1854026.333      535920.378
#Sta/Elev= 30
       0  615.26     8.3  615.22    16.6  614.41    24.9  612.09    33.2  608.58
    49.7  602.37    59.2  600.42    68.7  599.89    78.2   599.8   154.3  600.19
   163.8  599.92   182.9  598.14   201.9  599.05   220.9  598.82   239.9   597.2
   259.5  594.34   269.2  593.04     279   592.8   288.8  593.85   308.4  599.46
   318.1  599.54   327.9  599.06     367  598.43     455  597.98   464.8  598.35
   474.6  600.28   483.3  603.86   500.6  613.08   509.3  614.69     518  614.81
#Mann= 3 , 0 , 0
       0     .06       0   259.5    .045       0   288.8     .06       0
#XS Ineff= 2 , 0
          218.95  610.01  317.27          608.79
Permanent Ineff=
       F       F
Bank Sta=259.5,288.8
XS Rating Curve= 0 ,0
Exp/Cntr=0.3,0.1

Type RM Length L Ch R = 1 ,430.2   ,25.3,25.3,25.3
XS GIS Cut Line= 6
     1854488.139      536270.204     1854394.389      536155.621
     1854237.271      536087.913     1854176.507      536057.531
     1854053.367      535937.603       1854021.9      535900.711
#Sta/Elev= 30
       0  618.24    27.8  618.56      74  616.42   138.8  616.96     157  615.41
   165.9  613.84   174.8  611.52   210.6  606.83   237.6  601.52   246.7  600.49
   264.8  600.11     292  600.79   319.2  599.77   328.9     599   338.6   596.4
  344.73  594.17   348.3  593.03     358  592.84   367.7  594.11   377.4   597.9
   387.1  599.97     473  598.43   530.3  598.04   539.9  598.42   549.4  600.34
     559  604.25   568.7   609.1   578.4  612.78   588.1  614.15   607.5  614.49
#Mann= 3 , 0 , 0
       0     .06       0  344.73    .045       0   367.7     .06       0
#XS Ineff= 2 , 0
          313.73  608.37  385.03          609.36
Permanent Ineff=
       F       F
Bank Sta=344.73,367.7
XS Rating Curve= 0 ,0
Exp/Cntr=0.3,0.1

Type RM Length L Ch R = 1 ,405     ,98.5,101.1,103.7
XS GIS Cut Line= 6
     1854499.423      536247.635     1854405.673      536133.052
     1854248.555      536065.343     1854187.791      536034.961
     1854064.652      535915.034     1854033.185      535878.141
#Sta/Elev= 30
       0   620.3     9.2  619.98    27.8   618.4    64.8   616.2   101.8  616.62
   120.3  616.24   129.5   615.7   183.8   609.9   201.7  607.57   237.6  601.89
   246.7  601.07   264.8  600.62     301  600.58   328.9  599.44   338.6  597.71
   348.3  594.19     358  592.88   367.7     594   377.4  597.26   387.1  599.68
   396.6  599.95   434.8  599.24   530.3   598.3   539.9  599.11   549.4  601.76
     559  605.22   568.7  609.36   578.4  612.44   588.1  613.54   607.5  613.93
#Mann= 3 , 0 , 0
       0     .06       0   348.3    .045       0   367.7     .06       0
#XS Ineff= 2 , 0
                          388.13          607.68
Permanent Ineff=
       F       F
Bank Sta=348.3,367.7
XS Rating Curve= 0 ,0
Exp/Cntr=0.3,0.1

Type RM Length L Ch R = 1 ,303.9   ,143.1,147.8,152.5
XS GIS Cut Line= 4
     1854454.285      536094.857     1854277.201      535969.857
     1854229.458      535938.607     1854107.062      535847.461
#Sta/Elev= 30
       0  612.42     9.4  611.97    37.7  610.21    47.1  609.61    56.6  608.83
      66  607.93    84.8   605.7   122.5  601.45   131.9  600.58   141.4     600
   197.9  599.84   207.3   599.9   216.8  598.88   226.3  595.99   233.9  593.21
   235.8  592.52   245.3  591.76   248.9  592.67  250.22  593.09   254.8  594.16
   264.3  598.06   273.8  600.63   283.4  601.05   302.4  601.22     331  601.33
   359.7  601.82   369.2  601.88   407.4  601.97   416.9  601.89   426.4  601.44
#Mann= 3 , 0 , 0
       0     .06       0   233.9    .045       0  250.22     .06       0
Bank Sta=233.9,250.22
XS Rating Curve= 0 ,0
Exp/Cntr=0.3,0.1

Type RM Length L Ch R = 1 ,156.1   ,120,126.2,132.4
XS GIS Cut Line= 4
     1854548.159      536078.662     1854370.208      535873.584
     1854263.871      535767.247     1854143.428      535627.273
#Sta/Elev= 30
       0  614.23    19.4  613.68    58.2  614.39    77.6   613.8    87.3  613.82
   135.8  614.76   164.8  615.61   203.6  615.55   213.3  614.69   242.4  610.04
   252.1  608.96   261.8  608.32   271.5  608.07   280.9  606.12   290.3  603.49
   299.7  601.65   309.1  601.12   318.5  599.05  334.19  592.68   337.3  591.49
   346.7  590.86  357.75  593.37   365.5  598.43   374.9  602.28   384.3  603.78
   441.3  605.76   470.5  607.83   489.9  608.68   528.8  608.62   606.6  609.28
#Mann= 3 , 0 , 0
       0     .06       0  334.19    .045       0  357.75     .06       0
Bank Sta=334.19,357.75
XS Rating Curve= 0 ,0
Exp/Cntr=0.3,0.1

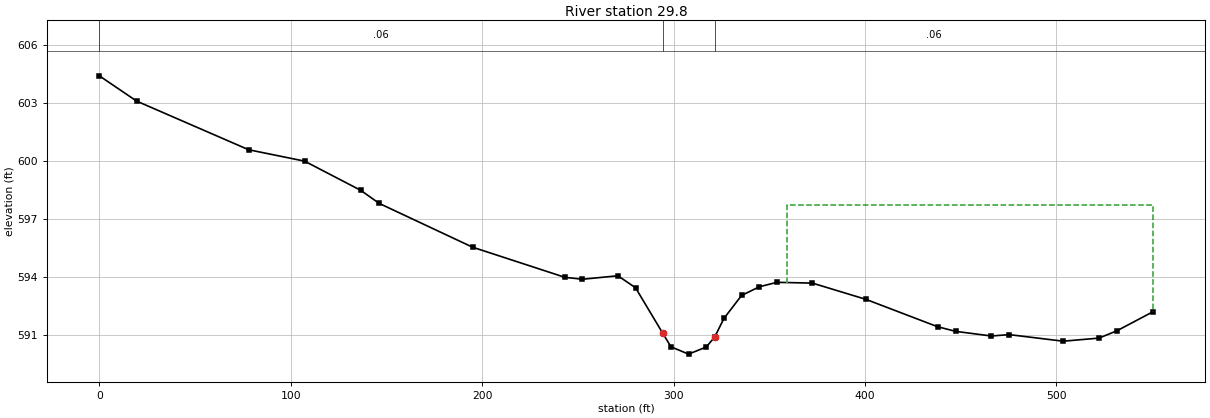
Type RM Length L Ch R = 1 ,29.8    ,38.1,29.8,21.6
XS GIS Cut Line= 4
     1854569.736      535967.253     1854428.677      535780.621
     1854354.892      535652.583     1854265.916      535509.354
#Sta/Elev= 30
       0  604.42    19.5  603.11      78  600.59   107.2     600   136.5  598.49
   146.2  597.81     195  595.54   243.2  593.98   252.4  593.88   270.9  594.06
   280.1  593.44   294.4  591.07   298.6  590.38   307.8     590   317.1  590.37
  321.52   590.9   326.3  591.85   335.5  593.04   344.8  593.49     354  593.72
   372.5  593.68   400.4  592.84   437.9  591.42   447.3  591.18     466  590.94
   475.4  591.01   503.5  590.67   522.2  590.83   531.6  591.21   550.3  592.19
#Mann= 3 , 0 , 0
       0     .06       0   294.4    .045       0  321.52     .06       0
#XS Ineff= 2 , 0
                          359.26          597.73
Permanent Ineff=
       F       F
Bank Sta=294.4,321.52
XS Rating Curve= 0 ,0
Exp/Cntr=0.3,0.1

Chan Stop Cuts=-1
Use User Specified Reach Order=0
Composite Channel Slope=5